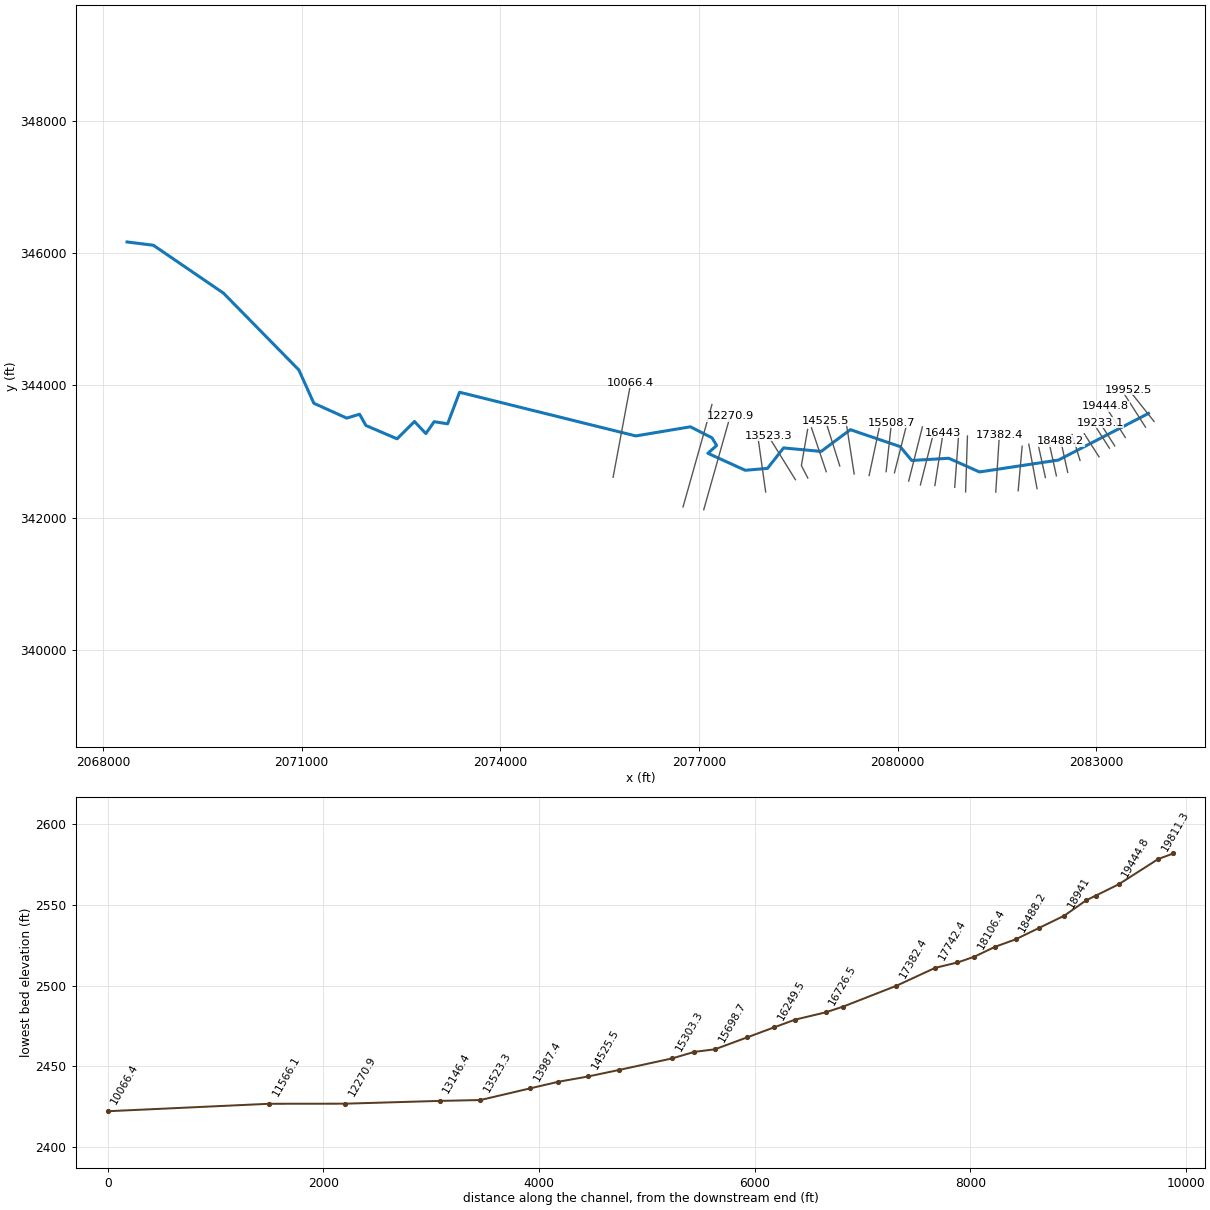
--- BeaverCk.prj (project) ---

Proj Title=BeaverCk
Current Plan=p01
Default Exp/Contr=0,0
English Units
Geom File=g01
Flow File=f01
Plan File=p01
BEGIN DESCRIPTION:
END DESCRIPTION:
DSS Export Rating Curves= 0
DSS Export Rating Curve Sorted= 0
DSS Export Volume Flow Curves= 0
DXF OffsetX= 0
DXF OffsetY= 0
DXF ScaleX= 0
DXF ScaleY= 0

--- BeaverCk.p01 (plan) ---

Plan Title=Floodplain
Program Version=4.00
Geom File=g01
Flow File=f01
K Sum by GR=0
Std Step Tol=0.01
Critical Tol=0.01
Num of Std Step Trials=20
Max Error Tol=0.3
Flow Tol Ratio=0.001
Split Flow NTrial=30
Split Flow Tol=0.02
Split Flow Ratio=0.02
Log Output Level=0
Friction Slope Method=1
Unsteady Friction Slope Method=2
Unsteady Bridges Friction Slope Method=1
Global Log Level=0
CheckData=False
Run HTab=0
Run UNet=0
Run PostProcess=0
UNET Theta=0
UNET Theta Warmup=0
UNET ZTol=0
UNET ZSATol=0
UNET MxIter=0
UNET MaxInSteps=0
UNET DtIC=0
UNET DtMin=0
UNET MaxCRTS=0
UNET WFStab=0
UNET SFStab=0
UNET WFX=0
UNET SFX=0
UNET DSS MLevel=0
UNET DZMax Abort=0
UNET Convert EG Bridges=0
UNET Use Existing IB Tables=0
UNET Froude Limit=0
UNET Froude Power=0
Write IC File=0
Echo Input=False
Echo Output=False
Write Detailed=0

--- BeaverCk.f01 (steady flow) ---

Flow Title=NFF Regression Equation
Program Version=4.00
Number of Profiles=1
Profile Names=P100yr
River Rch & RM=BeaverCk,Main      ,19952.5
481.6342
River Rch & RM=BeaverCk,Main      ,19811.3
653.5281
River Rch & RM=BeaverCk,Main      ,19233.1
657.4269
River Rch & RM=BeaverCk,Main      ,18941
739.9322
River Rch & RM=BeaverCk,Main      ,16890
809.1162
River Rch & RM=BeaverCk,Main      ,13523.3
871.4078
River Rch & RM=BeaverCk,Main      ,9129.8
966.3659
River Rch & RM=BeaverCk,Main      ,8490.8
1308.016
River Rch & RM=BeaverCk,Main      ,476.6
1421.618
Boundary for River Rch & Prof#=BeaverCk,Main      ,1
Up Type=0
Dn Type=3
Dn Slope=0.000218

--- BeaverCk.g01 (geometry) ---

Geom Title=USGS 10m DEM
Program Version=4.10

River Reach=BeaverCk        ,Main
Reach XY= 30
     2083788.683       343574.66     2082428.374      342868.981
     2081235.888      342688.918     2080772.281      342896.007
     2080212.242      342862.975     2080036.573      343073.177
     2079285.851      343328.423     2078844.426      342999.606
      2078276.88      343052.157     2078033.646      342742.859
     2077698.824      342714.332      2077134.28      342971.079
     2077266.407      343089.693      2077195.84      343205.304
     2076870.026      343371.965     2076044.231      343233.832
     2073383.671      343894.467     2073202.831      343417.091
     2072999.969      343449.122     2072874.515      343269.282
     2072702.349      343451.458     2072439.767      343190.094
     2071968.631      343391.913     2071873.552      343561.564
     2071679.365      343503.508     2071182.887      343727.723
     2070956.402      344231.452     2069817.574      345393.326
     2068758.576      346117.464     2068361.047      346166.894

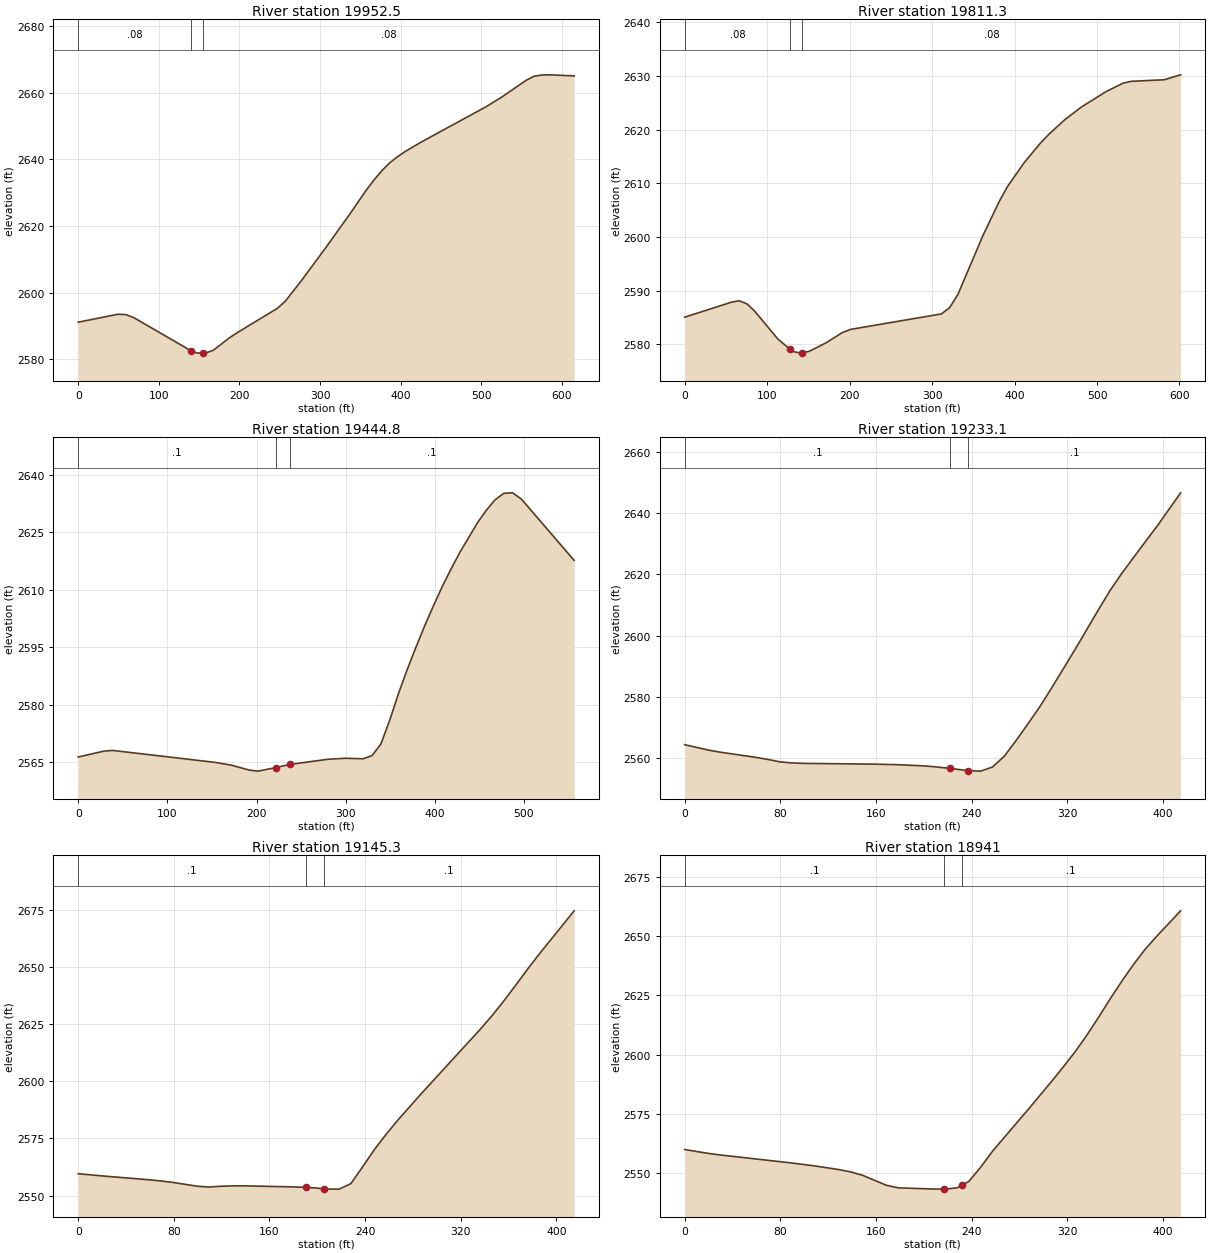
Type RM Length L Ch R = 1 ,19952.5 ,143.5,141.2,138.9
XS GIS Cut Line= 3
     2083872.739      343452.927     2083780.857      343568.434
     2083489.907      343934.199
#Sta/Elev= 30
       0 2591.11    49.2 2593.49      59  2593.4    68.9 2592.48   140.1  2582.5
   147.6 2581.86   155.1 2581.83   157.5 2581.82   167.5 2582.67   187.4 2586.39
   197.3 2587.98     247 2595.27     257 2597.46   276.9 2603.62   306.7 2613.39
   336.5 2623.46   356.4 2630.48   366.4 2633.69   376.3 2636.53   386.2 2638.94
   396.2 2640.83   406.1 2642.46     426 2645.28   505.6 2655.77   525.5 2658.74
   555.3 2663.71   565.2 2664.94   575.2 2665.34   585.1 2665.38     615 2665.06
#Mann= 3 , 0 , 0
       0     .08       0   140.1    .045       0   155.1     .08       0
Bank Sta=140.1,155.1
XS Rating Curve= 0 ,0
Exp/Cntr=0.3,0.1

Type RM Length L Ch R = 1 ,19811.3 ,365.7,366,366.3
XS GIS Cut Line= 3
     2083743.645       343366.01     2083667.484      343485.175
     2083419.774      343872.755
#Sta/Elev= 30
       0 2585.03    56.6 2587.82      66 2588.09    75.4 2587.53    84.8 2586.17
   113.1 2580.94   127.8 2579.05     132  2578.6   141.4 2578.33   142.8 2578.38
   151.4 2578.69   171.4 2580.25   191.4 2582.18   201.4 2582.76   311.4 2585.64
   321.4 2586.82   331.4 2589.29   361.4 2600.15   381.4 2606.58   391.4 2609.36
   411.4 2613.77   431.4 2617.48   441.4 2619.08   461.4  2621.9   481.4 2624.23
   511.4 2627.11   531.4 2628.63   541.4 2628.99   581.4 2629.28   601.4  2630.2
#Mann= 3 , 0 , 0
       0     .08       0   127.8    .045       0   142.8     .08       0
Bank Sta=127.8,142.8
XS Rating Curve= 0 ,0
Exp/Cntr=0.3,0.1

Type RM Length L Ch R = 1 ,19444.8 ,212.4,212.3,212.2
XS GIS Cut Line= 3
     2083438.722      343209.999     2083341.189      343363.513
     2083140.393       343679.56
#Sta/Elev= 30
       0 2566.39    28.7 2567.93    38.3 2568.12   153.2    2565   172.3 2564.24
   191.7 2562.99   201.6 2562.71   222.1 2563.65   237.1 2564.45   280.4 2565.81
   300.1 2566.07   319.8 2565.93   329.7 2566.78   339.5 2569.78   349.4 2575.98
   359.2 2582.92   369.1 2589.23     379 2595.12   388.8 2600.71   398.7 2605.96
   408.5 2610.93   418.4 2615.52   428.2 2619.81   447.9 2627.52   457.8 2630.78
   467.6 2633.49   477.5 2635.19   487.3 2635.31   497.2 2633.66   556.3 2617.69
#Mann= 3 , 0 , 0
       0      .1       0   222.1    .045       0   237.1      .1       0
Bank Sta=222.1,237.1
XS Rating Curve= 0 ,0
Exp/Cntr=0.3,0.1

Type RM Length L Ch R = 1 ,19233.1 ,87.6,87.7,87.8
XS GIS Cut Line= 3
     2083279.358      343082.035     2083172.406      343249.379
     2083055.905      343431.662
#Sta/Elev= 28
       0 2564.33    19.9 2562.57    29.8 2561.88    59.6 2560.19    69.5 2559.52
    79.4 2558.74    89.4 2558.37    99.3 2558.23   158.9 2557.97   178.7 2557.79
   198.6 2557.44   208.4 2557.15   222.2 2556.57   237.2 2555.83   247.8 2555.69
   257.6 2557.06   267.4 2560.57   277.3 2565.71   287.1 2571.09   296.9 2576.62
   306.8 2582.74   326.4 2595.32   346.1  2608.4   355.9 2614.74   365.8 2620.38
   385.4 2630.68   395.3 2635.78   414.9 2646.64
#Mann= 3 , 0 , 0
       0      .1       0   222.2    .045       0   237.2      .1       0
Bank Sta=222.2,237.2
XS Rating Curve= 0 ,0
Exp/Cntr=0.3,0.1

Type RM Length L Ch R = 1 ,19145.3 ,204.2,204.2,204.2
XS GIS Cut Line= 3
     2083198.354      343048.864     2083091.402      343216.208
     2082974.901      343398.491
#Sta/Elev= 29
       0  2559.6    19.9 2558.65    59.6 2556.94    69.5 2556.43    79.4 2555.78
    99.3 2554.16   109.2  2553.8   119.2 2554.12   129.1  2554.3     139  2554.3
   178.7 2553.86   190.8 2553.64   198.6 2553.37   205.8 2553.01   208.4 2552.88
   218.3 2552.87   228.1 2555.27   237.9 2562.58   247.8 2570.16   257.6 2576.81
   267.4 2583.02   287.1 2594.63   336.3 2622.68   346.1 2628.59   355.9    2635
   365.8 2641.84   375.6 2648.75   385.4  2655.4   414.9 2674.47
#Mann= 3 , 0 , 0
       0      .1       0   190.8    .045       0   205.8      .1       0
Bank Sta=190.8,205.8
XS Rating Curve= 0 ,0
Exp/Cntr=0.3,0.1

Type RM Length L Ch R = 1 ,18941   ,246,239.9,233.9
XS GIS Cut Line= 3
     2083041.294      342917.661     2082934.341      343085.005
      2082817.84      343267.288
#Sta/Elev= 30
       0 2559.99    19.9 2558.36    29.8  2557.7    89.4 2554.34   109.2 2553.06
   129.1 2551.54     139 2550.54     149  2549.1   168.8 2544.93   178.7 2543.85
   208.4 2543.35   216.8 2543.32   218.3 2543.31   228.1 2543.88   231.8 2544.92
   237.9 2546.64   247.8 2552.67   257.6 2559.33   287.1 2576.73   306.8 2588.61
   316.6 2594.72   326.4 2601.03   336.3 2608.06   346.1  2615.6   355.9 2623.43
   365.8 2631.01   375.6 2638.05   385.4 2644.49   395.3 2650.08   414.9 2660.59
#Mann= 3 , 0 , 0
       0      .1       0   216.8    .045       0   231.8      .1       0
Bank Sta=216.8,231.8
XS Rating Curve= 0 ,0
Exp/Cntr=0.3,0.1

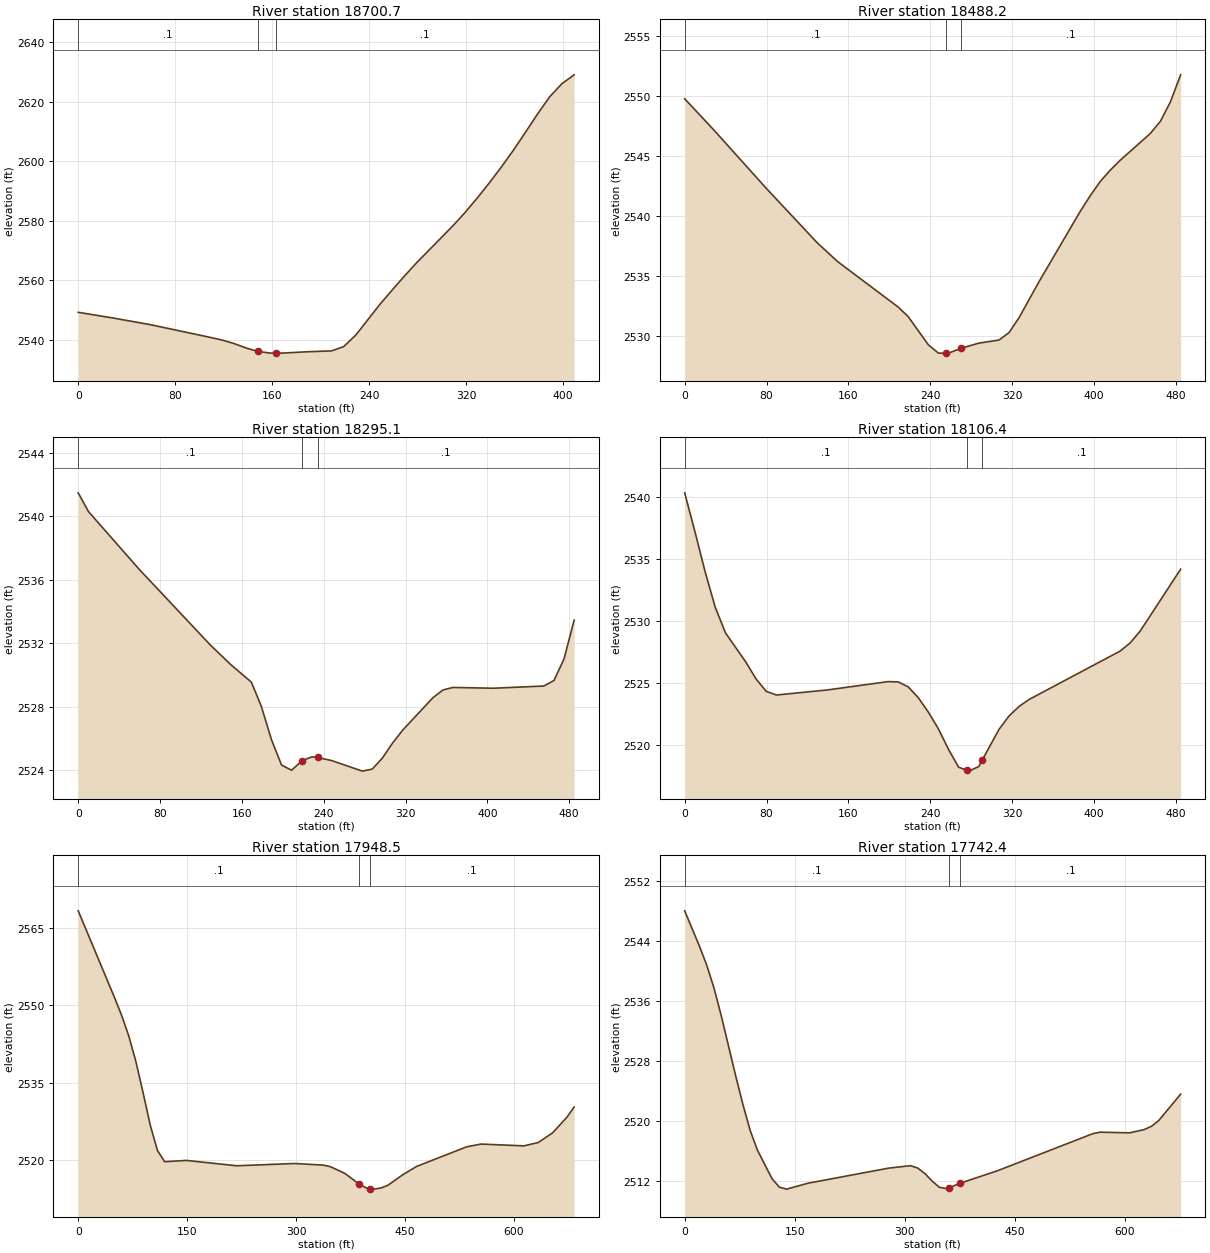
Type RM Length L Ch R = 1 ,18700.7 ,214.4,212.4,210.4
XS GIS Cut Line= 3
     2082754.557       342863.48     2082717.139       342986.83
     2082635.785      343255.019
#Sta/Elev= 30
       0 2549.23    29.8 2547.24    59.5 2545.08   109.1 2540.78     119 2539.88
   128.9 2538.67   138.9 2537.18   148.4 2536.06   158.9  2535.5   163.4 2535.51
   168.9 2535.52     189 2535.96     209 2536.25     219 2537.68     229 2541.56
     249 2551.93     259  2556.7     269 2561.34     279  2565.8   309.1  2578.3
   319.1 2582.75   329.1 2587.59   339.1  2592.7   349.1 2598.07   359.1 2603.76
   369.1 2609.81   379.1 2615.98   389.1 2621.77   399.2 2626.15   409.2  2629.1
#Mann= 3 , 0 , 0
       0      .1       0   148.4    .045       0   163.4      .1       0
Bank Sta=148.4,163.4
XS Rating Curve= 0 ,0
Exp/Cntr=0.3,0.1

Type RM Length L Ch R = 1 ,18488.2 ,193.3,193,192.7
XS GIS Cut Line= 3
     2082568.026      342683.973     2082538.031      342820.311
     2082463.858      343157.457
#Sta/Elev= 26
       0 2549.78    29.9 2547.05    79.8 2542.32   129.6 2537.79   149.5 2536.23
   208.6 2532.45   218.5 2531.65   238.2  2529.3   248.1 2528.61   255.4 2528.61
     258 2528.61   270.4 2529.02   287.5 2529.44   307.3  2529.7   317.1 2530.32
     327 2531.58   346.7  2534.6   386.2 2540.34     396 2541.65   405.9 2542.86
   415.8 2543.82   425.6 2544.65   455.2 2546.89   465.1 2547.91   474.9 2549.53
   484.8 2551.77
#Mann= 3 , 0 , 0
       0      .1       0   255.4    .045       0   270.4      .1       0
Bank Sta=255.4,270.4
XS Rating Curve= 0 ,0
Exp/Cntr=0.3,0.1

Type RM Length L Ch R = 1 ,18295.1 ,187.4,188.7,188.6
XS GIS Cut Line= 3
     2082397.561      342630.637     2082367.567      342766.974
     2082293.394      343104.121
#Sta/Elev= 27
       0 2541.49      10 2540.31    59.8 2536.65   129.6 2531.86   149.5 2530.63
   169.2 2529.55     179 2528.02   188.9 2525.92   198.8 2524.31   208.6 2523.99
   219.1  2524.6   228.4 2524.83   234.1 2524.79   248.1 2524.59   277.7 2523.93
   287.5 2524.06   297.4 2524.76   307.3  2525.7   317.1 2526.51   346.7 2528.56
   356.6 2529.05   366.4 2529.21   405.9 2529.16   455.2  2529.3   465.1 2529.65
   474.9 2531.01   484.8 2533.46
#Mann= 3 , 0 , 0
       0      .1       0   219.1    .045       0   234.1      .1       0
Bank Sta=219.1,234.1
XS Rating Curve= 0 ,0
Exp/Cntr=0.3,0.1

Type RM Length L Ch R = 1 ,18106.4 ,160.6,157.3,155.5
XS GIS Cut Line= 3
     2082231.647        342604.6     2082201.652      342740.938
     2082127.479      343078.084
#Sta/Elev= 30
       0 2540.34      10 2537.22    19.9    2534    29.9  2531.1    39.9 2529.04
    59.8 2526.69    69.8 2525.32    79.8 2524.32    89.7 2524.03   139.6 2524.44
   198.8 2525.11   208.6 2525.09   218.5 2524.69   228.4 2523.81   238.2 2522.65
   248.1 2521.29     258 2519.63   267.8 2518.21   275.9 2517.95   277.7 2517.89
   287.5 2518.26   290.9 2518.79   307.3 2521.26   317.1 2522.34     327 2523.12
   336.9 2523.68   425.6 2527.57   435.5 2528.23   445.4  2529.2   484.8 2534.18
#Mann= 3 , 0 , 0
       0      .1       0   275.9    .045       0   290.9      .1       0
Bank Sta=275.9,290.9
XS Rating Curve= 0 ,0
Exp/Cntr=0.3,0.1

Type RM Length L Ch R = 1 ,17948.5 ,211.8,206.7,201.5
XS GIS Cut Line= 3
     2082105.166       342437.04     2082034.816      342817.813
     2081981.066      343108.739
#Sta/Elev= 30
       0 2568.39    49.6 2551.67    59.6 2548.14    69.5 2544.13    79.4 2539.11
    89.4 2533.01    99.3 2526.69   109.2 2521.79   119.1 2519.62   148.9 2519.87
   218.4 2518.83   297.9 2519.27   337.6 2518.96   347.5 2518.65   367.4 2517.34
   387.3 2515.22   397.1  2514.5   402.3 2514.39   406.9 2514.29   416.8  2514.5
   426.7 2515.05   446.4 2517.03   466.1  2518.7   535.1 2522.52   554.9 2523.05
     614  2522.7   633.8 2523.36   653.5 2525.24   673.2 2528.28   683.1 2530.26
#Mann= 3 , 0 , 0
       0      .1       0   387.3    .045       0   402.3      .1       0
Bank Sta=387.3,402.3
XS Rating Curve= 0 ,0
Exp/Cntr=0.3,0.1

Type RM Length L Ch R = 1 ,17742.4 ,359.5,360,360.7
XS GIS Cut Line= 3
     2081820.328      342404.612     2081850.291      342740.598
     2081880.363       343077.79
#Sta/Elev= 30
       0 2548.01    19.8 2543.38    29.8 2540.85    39.7 2537.82    49.6 2534.15
    69.4 2526.09    79.4 2522.22    89.3 2518.76    99.2 2516.15     119 2512.37
     129 2511.23   138.9 2510.97   168.7 2511.77   277.8 2513.76   307.6 2514.09
   317.5 2513.78   327.4 2513.04   337.3 2512.03   347.3  2511.2   357.2 2511.04
   360.8 2511.17   375.8 2511.77   426.9 2513.44   556.4 2518.36   566.3 2518.55
   606.2 2518.46   626.1 2518.89     636 2519.33     646  2520.1   675.8 2523.61
#Mann= 3 , 0 , 0
       0      .1       0   360.8    .045       0   375.8      .1       0
#XS Ineff= 2 , 0
          307.53 2514.05
Permanent Ineff=
       F       F
Bank Sta=360.8,375.8
XS Rating Curve= 0 ,0
Exp/Cntr=0.3,0.1

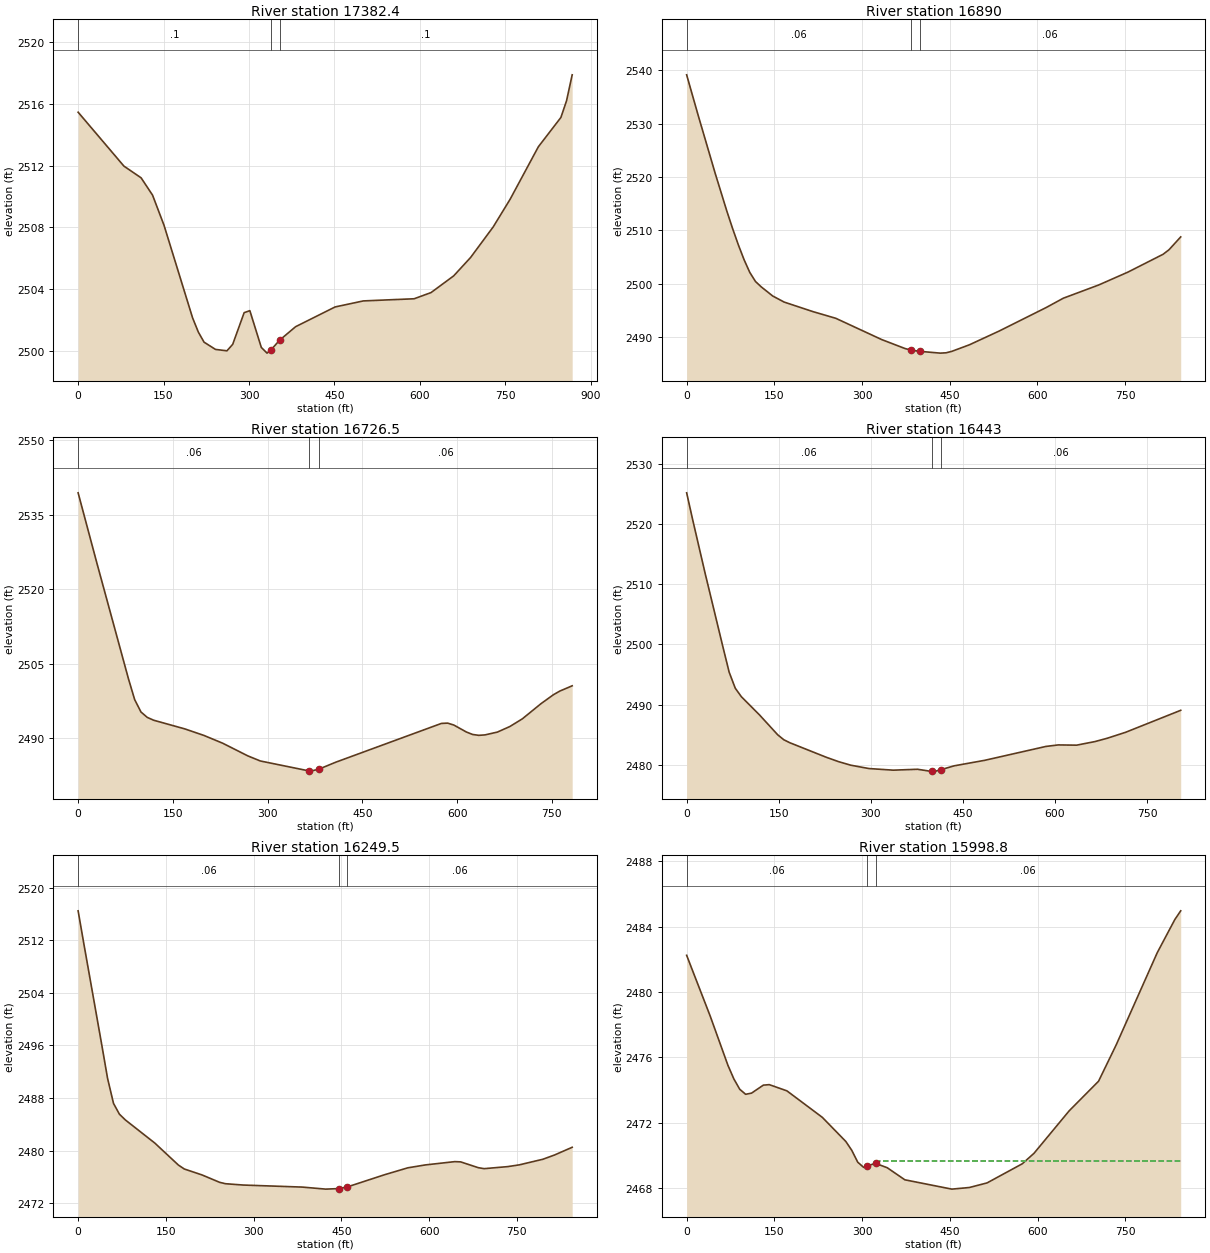
Type RM Length L Ch R = 1 ,17382.4 ,489.5,492.3,495
XS GIS Cut Line= 3
     2081482.025      342385.266     2081505.325      342756.404
     2081536.375      343250.995
#Sta/Elev= 30
       0 2515.46    80.4 2511.97   110.6 2511.21   130.7 2510.09   150.8 2508.14
     201 2502.14   211.1 2501.22   221.1 2500.57   241.2  2500.1   261.3 2500.01
   271.4 2500.43   291.5 2502.48   301.5 2502.61   321.6 2500.23   331.7 2499.86
   338.8 2500.08   353.8  2500.7   381.8 2501.57   451.2 2502.85   500.7 2503.24
   589.9 2503.38   619.6 2503.78   659.3 2504.86     689 2506.05   728.7 2508.03
   758.4 2509.82     808 2513.22   847.6 2515.12   857.5  2516.2   867.4 2517.88
#Mann= 3 , 0 , 0
       0      .1       0   338.8    .045       0   353.8      .1       0
Bank Sta=338.8,353.8
XS Rating Curve= 0 ,0
Exp/Cntr=0.3,0.1

Type RM Length L Ch R = 1 ,16890   ,165.7,163.5,161.7
XS GIS Cut Line= 3
     2081026.286      342387.583     2081037.634      342730.904
      2081054.21       343232.41
#Sta/Elev= 30
       0 2539.12    19.6 2531.58    49.1 2520.58    68.7 2513.63    78.5 2510.38
    88.3 2507.33    98.2 2504.52     108 2502.13   117.8 2500.42   127.6 2499.42
   147.2 2497.71   166.8 2496.57   215.9 2494.79   255.2 2493.53   333.7 2489.55
   373.6 2487.87   383.4 2487.59   398.4 2487.35   433.8 2487.01   443.9 2487.07
   453.9 2487.35     484 2488.58   534.2 2491.12   614.5 2495.51   644.6  2497.3
   704.8 2499.76     755 2502.18   815.2 2505.52   825.2 2506.36   845.3 2508.77
#Mann= 3 , 0 , 0
       0     .06       0   383.4    .045       0   398.4     .06       0
Bank Sta=383.4,398.4
XS Rating Curve= 0 ,0
Exp/Cntr=0.3,0.1

Type RM Length L Ch R = 1 ,16726.5 ,285.6,282.9,279.8
XS GIS Cut Line= 3
     2080862.045      342456.903     2080889.347      342823.991
     2080920.053      343236.854
#Sta/Elev= 30
       0 2539.42    29.8 2525.24    79.6 2502.04    89.5 2497.82    99.5 2495.32
   109.4 2494.24   119.4 2493.67   169.1 2491.91     199 2490.61   228.8 2489.04
   268.6 2486.49   288.5 2485.46     366 2483.45   368.1 2483.42     381 2483.81
   407.5  2485.2   575.1 2493.02     585 2493.08   594.8 2492.69   614.5  2491.3
   624.4  2490.8   634.2 2490.62   644.1 2490.71   663.8 2491.28   683.5  2492.4
   703.2 2493.94   732.8    2497   752.5  2498.8   762.4 2499.52   782.1 2500.59
#Mann= 3 , 0 , 0
       0     .06       0     366    .045       0     381     .06       0
Bank Sta=366,381
XS Rating Curve= 0 ,0
Exp/Cntr=0.3,0.1

Type RM Length L Ch R = 1 ,16443   ,196.5,193.7,190.9
XS GIS Cut Line= 3
     2080562.509      342484.616     2080624.907      342885.525
     2080686.284      343279.876
#Sta/Elev= 30
       0 2525.23     9.9 2520.72    29.7 2512.01    59.4 2499.46    69.3 2495.37
    79.2 2492.72    89.1 2491.31   118.8 2488.26   148.4 2484.96   158.3 2484.14
   168.2 2483.64   227.6 2481.22   247.4  2480.5   267.2 2479.91   296.9 2479.35
   336.5 2479.08     376 2479.23   395.8 2478.92   399.2 2478.92   405.7 2478.92
   414.2 2479.16   435.7  2479.8   485.6 2480.72   585.3 2483.03   605.3 2483.28
   635.2 2483.24   665.2 2483.84   685.1 2484.39     715 2485.38   804.8 2489.04
#Mann= 3 , 0 , 0
       0     .06       0   399.2    .045       0   414.2     .06       0
Bank Sta=399.2,414.2
XS Rating Curve= 0 ,0
Exp/Cntr=0.3,0.1

Type RM Length L Ch R = 1 ,16249.5 ,250.5,250.7,251
XS GIS Cut Line= 3
     2080343.662      342493.034     2080435.154      342854.678
      2080550.79      343311.757
#Sta/Elev= 30
       0 2516.46    10.1  2511.3    40.3 2496.15    50.4 2490.97    60.5 2487.19
    70.6 2485.55    80.7 2484.68   131.1 2481.16   171.4 2477.82   181.5 2477.22
   211.7 2476.32     242 2475.19     252 2474.98   282.3 2474.78   383.1 2474.47
   423.2 2474.16   445.3 2474.24   460.3  2474.5   523.5 2476.34   563.6  2477.4
   593.7 2477.84   643.9 2478.34   653.9  2478.3     684 2477.42     694 2477.27
   734.2 2477.58   754.2 2477.85   794.4  2478.7   814.4 2479.35   844.5 2480.52
#Mann= 3 , 0 , 0
       0     .06       0   445.3    .045       0   460.3     .06       0
Bank Sta=445.3,460.3
XS Rating Curve= 0 ,0
Exp/Cntr=0.3,0.1

Type RM Length L Ch R = 1 ,15998.8 ,296.2,299.7,303.2
XS GIS Cut Line= 3
     2080166.762      342551.182     2080258.254      342912.826
      2080373.89      343369.906
#Sta/Elev= 30
       0 2482.25    40.3 2478.53    70.6 2475.52    80.7 2474.69    90.7 2474.06
   100.8 2473.75   110.9 2473.82   131.1 2474.31   141.2 2474.34   171.4 2473.96
   231.9 2472.34   272.2 2470.86   282.3 2470.32   292.4  2469.6   302.5 2469.28
   308.2 2469.38   323.2 2469.52   342.8 2469.26     373 2468.52   453.3 2467.95
   483.4 2468.05   513.5 2468.33   573.7  2469.5   593.7 2470.14   653.9 2472.74
   704.1 2474.55   734.2 2476.77   804.4 2482.41   834.5 2484.44   844.5 2484.97
#Mann= 3 , 0 , 0
       0     .06       0   308.2    .045       0   323.2     .06       0
#XS Ineff= 2 , 0
                          328.07         2469.67
Permanent Ineff=
       F       F
Bank Sta=308.2,323.2
XS Rating Curve= 0 ,0
Exp/Cntr=0.3,0.1

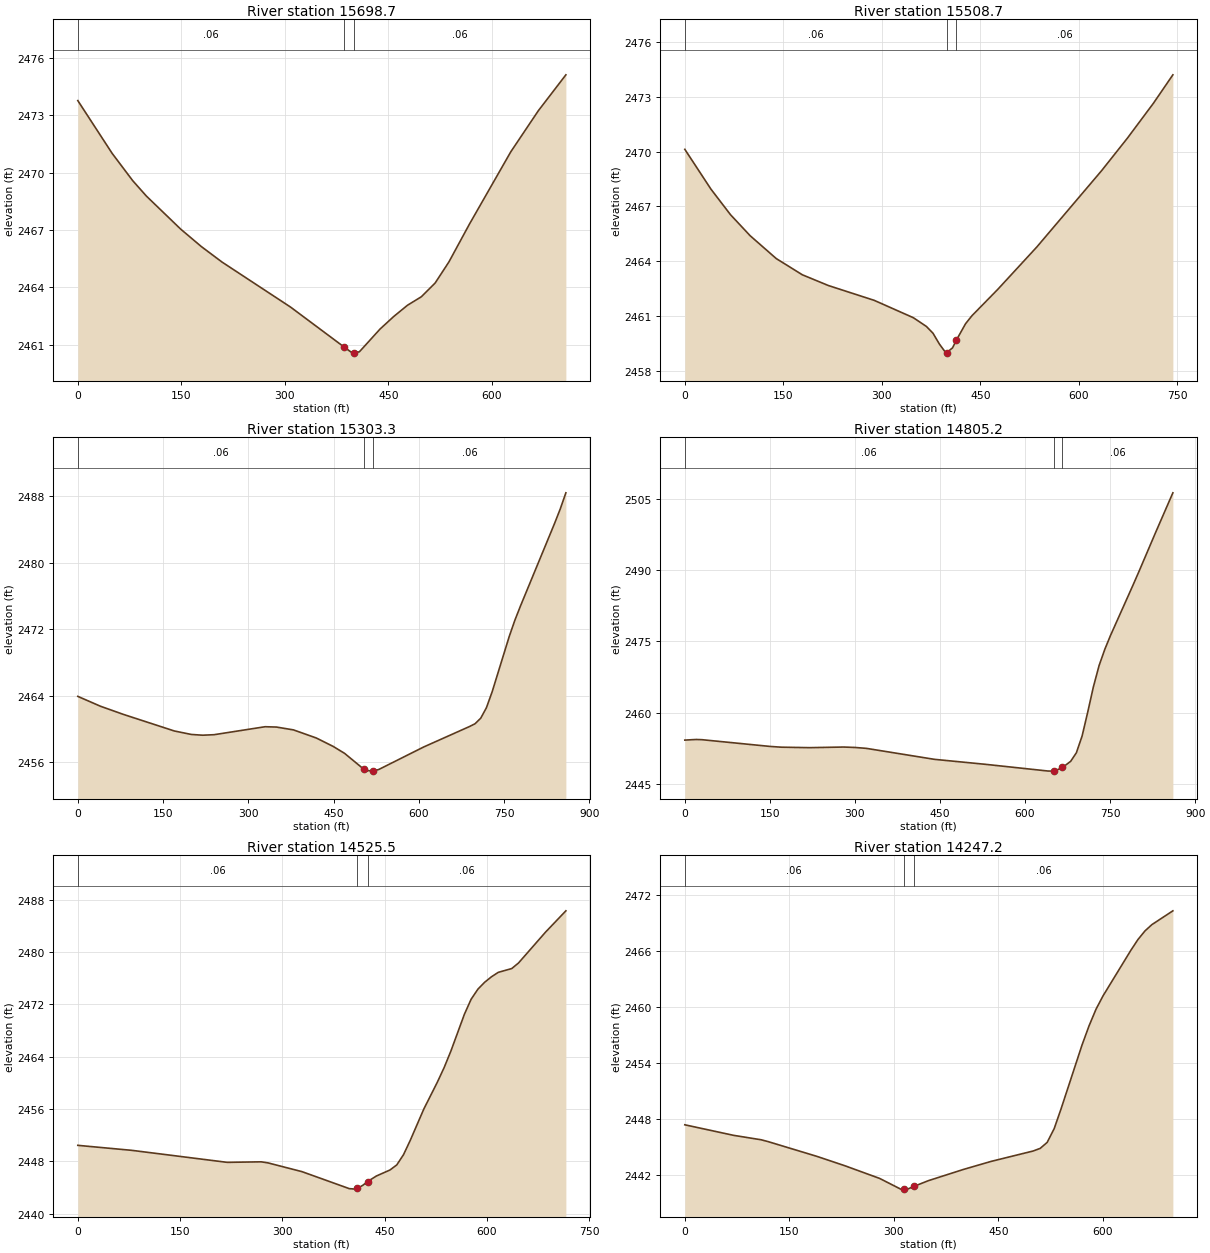
Type RM Length L Ch R = 1 ,15698.7 ,190.5,190.3,190.1
XS GIS Cut Line= 3
     2079951.653      342675.706     2080029.674      342984.105
     2080125.056      343361.123
#Sta/Elev= 22
       0 2473.77    49.7 2471.01    79.5 2469.58    99.4 2468.77   149.1 2467.04
   178.9 2466.13   208.8 2465.32   308.2 2462.96     385 2460.89   397.9 2460.55
     400 2460.56   407.9 2460.62   437.8 2461.81   457.7 2462.47   477.7 2463.06
   497.6  2463.5   517.6 2464.22   537.5 2465.32   567.4 2467.31   627.2 2471.09
   667.1 2473.24     707 2475.12
#Mann= 3 , 0 , 0
       0     .06       0     385    .045       0     400     .06       0
Bank Sta=385,400
XS Rating Curve= 0 ,0
Exp/Cntr=0.3,0.1

Type RM Length L Ch R = 1 ,15508.7 ,207.6,205.4,203.1
XS GIS Cut Line= 3
     2079825.952      342693.304     2079870.163      343098.718
     2079906.538      343432.269
#Sta/Elev= 24
       0 2470.12    39.8 2467.94    69.6 2466.54    99.5 2465.39   139.2 2464.14
     179 2463.25   218.8 2462.66   288.5 2461.85   348.1  2460.9     368 2460.42
     378 2460.05   387.9 2459.45   397.9 2458.96   398.6 2458.98   407.8 2459.25
   413.6 2459.67   427.6 2460.57   437.4 2461.01   476.9 2462.46   536.1 2464.77
   634.8 2468.95   674.3 2470.74   713.7 2472.64   743.4  2474.2
#Mann= 3 , 0 , 0
       0     .06       0   398.6    .045       0   413.6     .06       0
Bank Sta=398.6,413.6
XS Rating Curve= 0 ,0
Exp/Cntr=0.3,0.1

Type RM Length L Ch R = 1 ,15303.3 ,490.3,498.1,506.3
XS GIS Cut Line= 2
     2079569.144      342634.999      2079747.93      343475.127
#Sta/Elev= 30
       0 2463.91      40 2462.72    79.9 2461.75   169.8 2459.75   199.8 2459.33
   219.7 2459.24   239.7  2459.3   329.6 2460.26   349.6 2460.22   379.5 2459.88
   419.5 2458.91   449.4 2457.89   469.4 2457.06   499.4 2455.37   504.1  2455.2
   509.4    2455   519.1 2454.92   529.4 2455.11   609.2 2457.84   689.2 2460.28
   699.1 2460.62   709.1 2461.29   719.1 2462.55   729.1 2464.45   759.1 2471.09
     769 2473.04     779 2474.78     839 2484.71     849 2486.45   858.9 2488.39
#Mann= 3 , 0 , 0
       0     .06       0   504.1    .045       0   519.1     .06       0
Bank Sta=504.1,519.1
XS Rating Curve= 0 ,0
Exp/Cntr=0.3,0.1

Type RM Length L Ch R = 1 ,14805.2 ,275.7,279.6,283.2
XS GIS Cut Line= 2
      2079343.49      342657.982     2079211.215      343508.428
#Sta/Elev= 29
       0 2454.22      20 2454.35      30 2454.31   150.1 2452.89   170.1 2452.73
   220.2 2452.63   280.2 2452.76   300.2 2452.67   320.2 2452.48   440.3 2450.17
   530.4 2449.12   640.5 2447.71   650.5 2447.69   650.7  2447.7   660.5 2448.15
   665.7 2448.52   670.5 2448.86   680.5 2449.76   690.5 2451.55   700.6 2455.07
   710.6 2460.14   720.6 2465.47   730.6 2469.92   740.6 2473.31   750.6 2476.22
   790.6  2486.9   800.6 2489.63   830.6 2498.02   860.7 2506.27
#Mann= 3 , 0 , 0
       0     .06       0   650.7    .045       0   665.7     .06       0
Bank Sta=650.7,665.7
XS Rating Curve= 0 ,0
Exp/Cntr=0.3,0.1

Type RM Length L Ch R = 1 ,14525.5 ,279.7,278.3,274.8
XS GIS Cut Line= 3
     2079125.884      342779.935     2079024.383      343103.216
     2078911.402      343463.061
#Sta/Elev= 30
       0 2450.44    79.7 2449.67   219.2 2447.84   269.1 2447.92     279 2447.76
   328.9 2446.42   398.4 2443.82   408.3 2443.75   410.1 2443.86   418.2 2444.34
   425.1 2444.91   438.1 2445.76   457.9 2446.67   467.9 2447.45   477.8 2449.01
   487.7  2451.2   507.6 2455.99   527.4 2460.08   537.4 2462.32   547.3 2464.84
   567.1 2470.46     577 2472.76     587 2474.31   596.9 2475.36   606.8 2476.19
   616.8 2476.87   636.6 2477.45   646.5  2478.3   686.2 2483.02     716 2486.27
#Mann= 3 , 0 , 0
       0     .06       0   410.1    .045       0   425.1     .06       0
Bank Sta=410.1,425.1
XS Rating Curve= 0 ,0
Exp/Cntr=0.3,0.1

Type RM Length L Ch R = 1 ,14247.2 ,268.6,260.5,252.3
XS GIS Cut Line= 3
     2078921.542      342692.875     2078822.851      342986.209
     2078698.223      343356.631
#Sta/Elev= 28
       0 2447.35    69.9 2446.22   109.8 2445.74   119.8 2445.54   189.7 2443.96
   229.6 2442.96   279.5  2441.6   309.5 2440.46   313.9 2440.46   319.5 2440.45
   328.9 2440.75   349.6 2441.36   399.7 2442.56   439.8 2443.43   499.9 2444.54
   509.9 2444.82   519.9 2445.46     530 2446.94     540 2449.09     570 2455.92
   580.1 2457.98   590.1 2459.76   600.1 2461.18   640.2 2466.09   650.2 2467.22
   660.2 2468.14   670.2 2468.82   700.3  2470.3
#Mann= 3 , 0 , 0
       0     .06       0   313.9    .045       0   328.9     .06       0
Bank Sta=313.9,328.9
XS Rating Curve= 0 ,0
Exp/Cntr=0.3,0.1

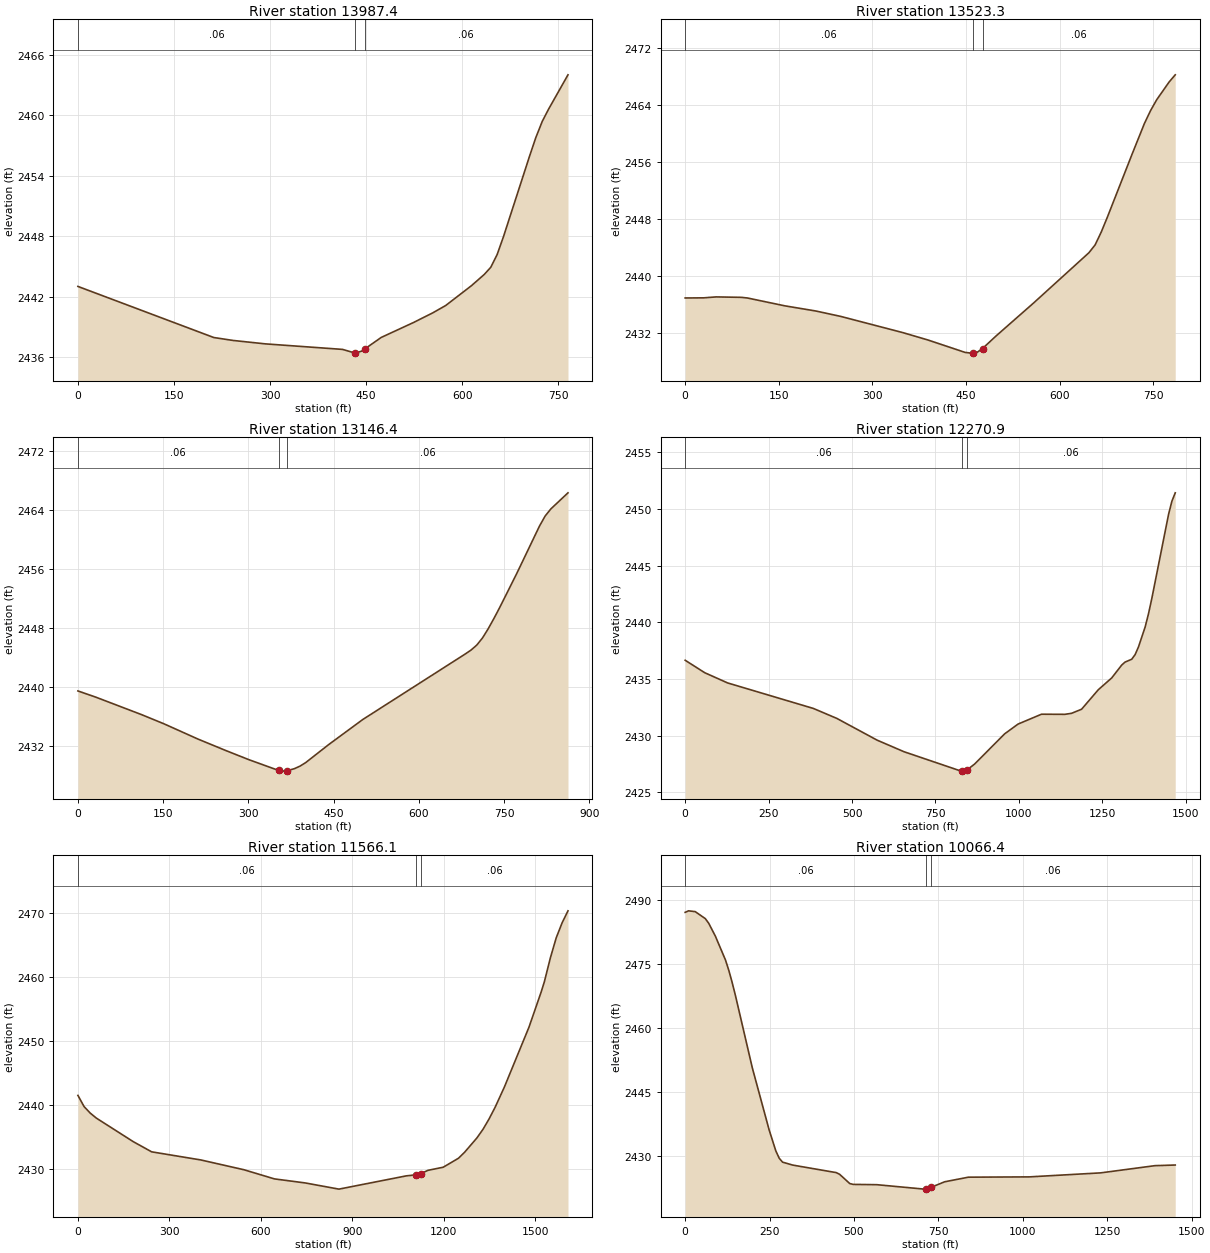
Type RM Length L Ch R = 1 ,13987.4 ,448.7,463.1,477.2
XS GIS Cut Line= 3
     2078643.059      342597.348     2078546.142      342786.073
     2078640.328      343331.056
#Sta/Elev= 23
       0 2443.01   212.2 2437.93   242.3 2437.64   292.6  2437.3   413.3 2436.75
   432.6 2436.39   433.4 2436.38   443.4 2436.59   447.6 2436.78   473.6 2437.94
   523.9 2439.42     554 2440.38   574.2 2441.11   614.4 2443.08   634.5  2444.2
   644.6 2444.91   654.6 2446.18   664.7    2448   704.9  2455.9   714.9 2457.79
     725 2459.41     735 2460.64   765.2 2464.04
#Mann= 3 , 0 , 0
       0     .06       0   432.6    .045       0   447.6     .06       0
Bank Sta=432.6,447.6
XS Rating Curve= 0 ,0
Exp/Cntr=0.3,0.1

Type RM Length L Ch R = 1 ,13523.3 ,386.4,377.1,368.6
XS GIS Cut Line= 3
       2078455.9      342572.091     2078172.938      343030.177
     2078043.162       343240.27
#Sta/Elev= 27
       0 2436.88    29.9  2436.9    49.8 2437.03    89.7 2436.97    99.7 2436.88
   159.5 2435.78   209.4 2435.05   249.3 2434.29     349 2432.01   388.9 2430.98
   448.7 2429.23   458.7 2429.13   461.6 2429.17   468.6 2429.28   476.6 2429.78
   498.6 2431.57   558.2 2436.16   647.1 2443.24     657 2444.34   666.8 2446.14
   676.7 2448.25   716.2 2457.08     736  2461.4   745.9 2463.22   755.7 2464.74
   775.5 2467.22   785.4 2468.24
#Mann= 3 , 0 , 0
       0     .06       0   461.6    .045       0   476.6     .06       0
Bank Sta=461.6,476.6
XS Rating Curve= 0 ,0
Exp/Cntr=0.3,0.1

Type RM Length L Ch R = 1 ,13146.4 ,843.5,875.2,869.3
XS GIS Cut Line= 4
     2078006.847      342386.464     2078005.201      342398.141
     2077956.497      342743.667     2077886.509       343240.18
#Sta/Elev= 27
       0 2439.48    31.7 2438.63   111.5 2436.28   151.4 2435.02   211.2 2432.95
     261 2431.37   300.9 2430.15   353.2 2428.69   360.7  2428.6   368.2 2428.66
   380.8 2428.93   390.8 2429.28   400.8 2429.76     441 2432.19   501.1  2435.6
   681.6  2444.5   691.7 2445.03   701.7  2445.7   711.7 2446.66   721.8 2447.91
   731.8  2449.3   741.8 2450.76   771.9 2455.39     812 2461.84     822 2463.21
   832.1 2464.18   862.2 2466.36
#Mann= 3 , 0 , 0
       0     .06       0   353.2    .045       0   368.2     .06       0
Bank Sta=353.2,368.2
XS Rating Curve= 0 ,0
Exp/Cntr=0.3,0.1

Type RM Length L Ch R = 1 ,12270.9 ,723.2,704.8,709.3
XS GIS Cut Line= 4
     2077071.227      342117.653     2077150.921      342400.089
     2077298.544      342923.264     2077469.993      343530.877
#Sta/Elev= 30
       0 2436.66    58.7 2435.56   127.2 2434.66   384.1 2432.41   454.5 2431.53
   575.3 2429.61   655.9 2428.59     827 2426.88   828.7 2426.88   843.7 2426.97
   867.1  2427.5   957.3 2430.17   997.4 2431.03  1067.6  2431.9  1137.7 2431.89
  1157.8 2431.98  1187.8 2432.34  1237.9 2434.06    1278  2435.1  1308.1 2436.24
  1318.1  2436.5  1338.1 2436.75  1348.2 2437.16  1358.2 2437.83  1378.2 2439.59
  1388.2 2440.75  1398.3 2442.12  1448.4 2449.53  1458.4 2450.69  1468.4 2451.43
#Mann= 3 , 0 , 0
       0     .06       0   828.7    .045       0   843.7     .06       0
Bank Sta=828.7,843.7
XS Rating Curve= 0 ,0
Exp/Cntr=0.3,0.1

Type RM Length L Ch R = 1 ,11566.1 ,1492,1499.6,1493.3
XS GIS Cut Line= 5
     2076758.645      342159.894     2076909.211        342693.5
     2077056.834      343216.676     2077176.949      343642.363
     2077195.316      343707.455
#Sta/Elev= 30
       0  2441.5    20.2 2439.75    40.3 2438.73    60.5 2437.94   181.4 2434.26
   241.9 2432.66   403.2 2431.39   544.4 2429.86     645 2428.42   745.7 2427.79
   856.4 2426.82  1077.9  2428.9  1110.2 2429.06  1125.2 2429.24  1148.3 2429.76
  1198.6 2430.25  1248.8 2431.66  1268.9  2432.6  1309.2 2434.84  1329.2 2436.19
  1349.4 2437.84  1369.5  2439.7  1399.6 2442.84    1480 2452.18  1520.2 2457.72
  1530.3 2459.26    1550    2463  1569.3 2466.16  1588.7 2468.52    1608  2470.4
#Mann= 3 , 0 , 0
       0     .06       0  1110.2    .045       0  1125.2     .06       0
Bank Sta=1110.2,1125.2
XS Rating Curve= 0 ,0
Exp/Cntr=0.3,0.1

Type RM Length L Ch R = 1 ,10066.4 ,461.4,457.8,454.9
XS GIS Cut Line= 3
     2075702.465      342609.301     2075792.013      343088.352
     2075969.157      344036.019
#Sta/Elev= 30
       0 2487.08      10 2487.44    29.8 2487.25    59.7 2485.61    69.6 2484.54
    89.5  2481.5   119.4 2475.91   129.3 2473.48   139.2 2470.63   149.2 2467.48
   198.9 2450.62   248.6 2436.11   268.5 2431.16   278.5 2429.45   288.4 2428.53
   318.3 2427.84   447.6 2426.07   457.5 2425.67   487.4 2423.51   497.4 2423.31
   567.7 2423.24   708.3  2422.2   713.8 2422.24   728.8 2422.64   768.5 2423.92
   838.8    2425  1019.6 2425.07  1230.5 2426.01  1391.2  2427.7  1451.4 2427.85
#Mann= 3 , 0 , 0
       0     .06       0   713.8    .045       0   728.8     .06       0
Bank Sta=713.8,728.8
XS Rating Curve= 0 ,0
Exp/Cntr=0.3,0.1