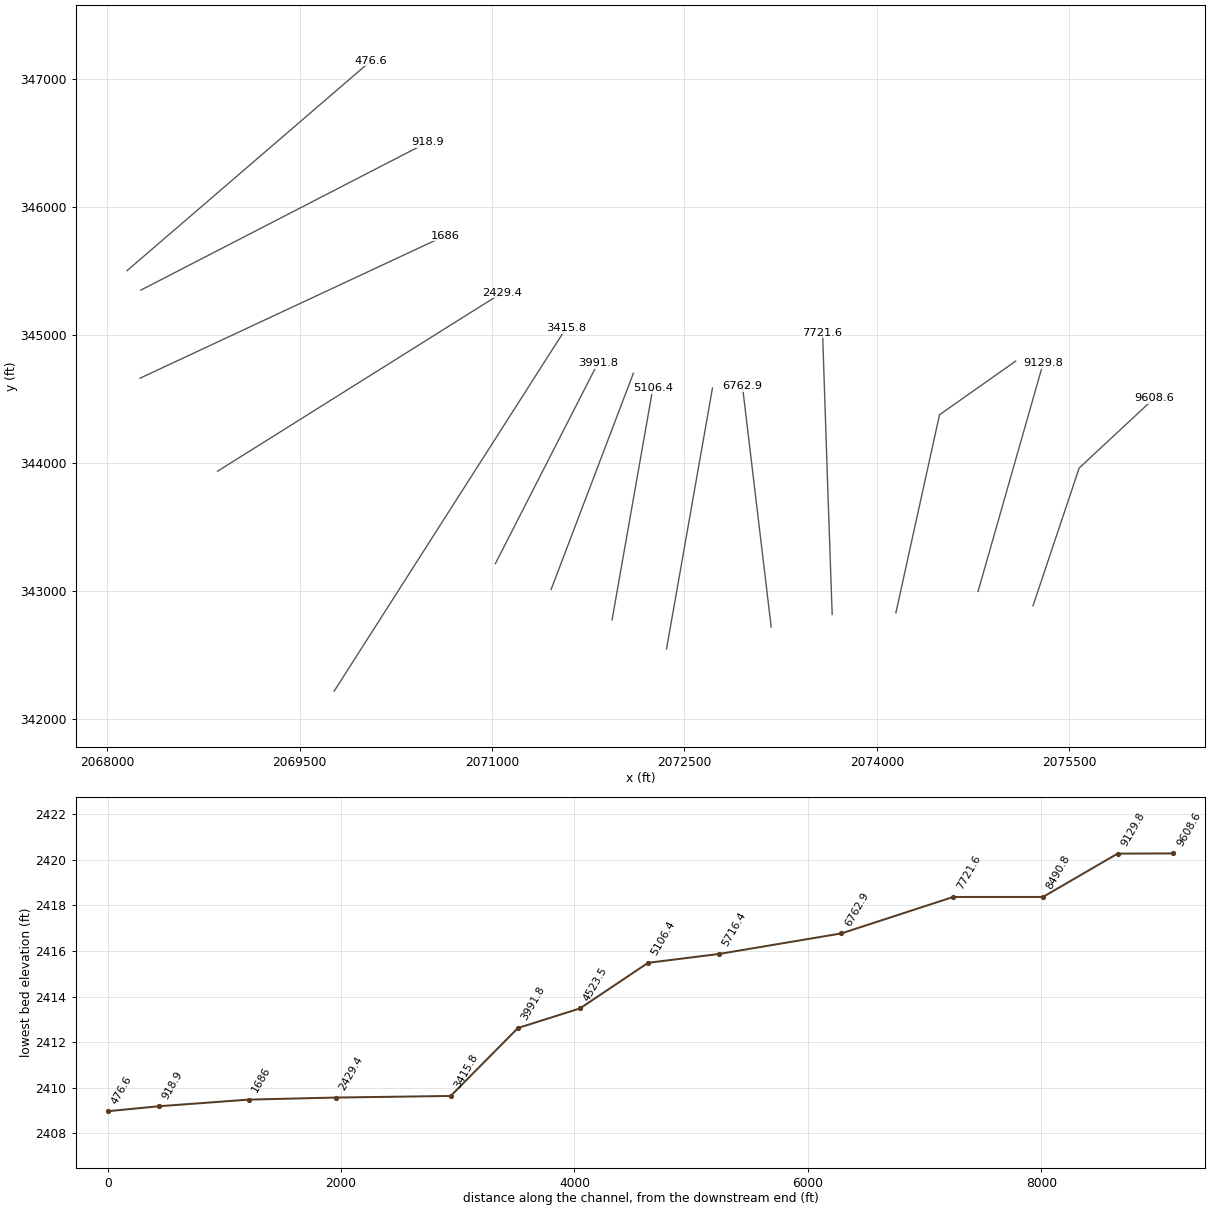
HEC-RAS study BeaverCk.prj: BeaverCk

--- BeaverCk.g01 (geometry) --- (continued)

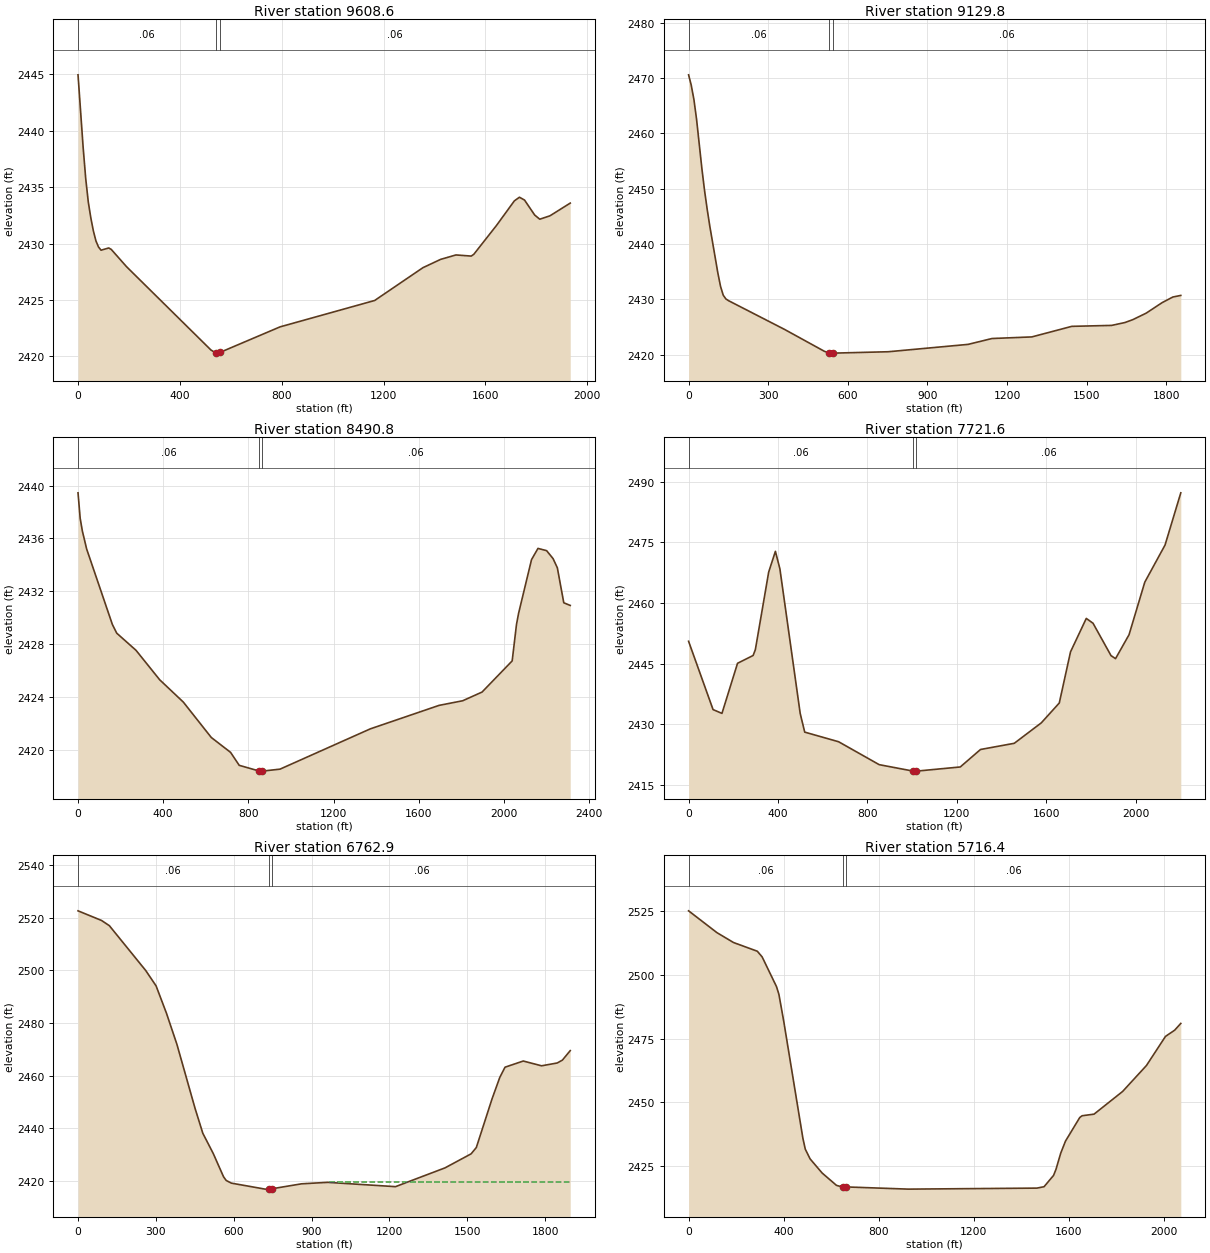
Type RM Length L Ch R = 1 ,9608.6  ,477.2,478.8,480.4
XS GIS Cut Line= 3
     2075217.653      342887.327     2075577.638      343963.924
     2076161.373      344508.125
#Sta/Elev= 30
       0 2444.97    20.1 2438.53    30.1 2435.79    40.2 2433.71    50.2 2432.29
    60.3 2431.12    70.3 2430.24    80.4  2429.7    90.4 2429.41   120.6 2429.61
   130.6 2429.48   190.9 2427.94   522.4 2420.55   542.2 2420.28   557.2 2420.34
   793.6 2422.61  1165.1 2424.95  1354.6 2427.86  1424.5  2428.6  1484.3 2428.99
  1544.2 2428.89  1554.2 2429.04    1644 2431.62  1713.8 2433.79  1733.7 2434.11
  1753.7 2433.86  1793.6 2432.53  1813.5 2432.16  1853.4 2432.46  1933.2 2433.59
#Mann= 3 , 0 , 0
       0     .06       0   542.2    .045       0   557.2     .06       0
Bank Sta=542.2,557.2
XS Rating Curve= 0 ,0
Exp/Cntr=0.3,0.1

Type RM Length L Ch R = 1 ,9129.8  ,637.5,638.9,640.3
XS GIS Cut Line= 3
     2074789.192      342999.127     2074932.205      343501.369
     2075297.258      344783.391
#Sta/Elev= 30
       0 2470.57      10  2468.7    20.1  2466.1    30.1 2462.52    50.2 2453.59
    60.2 2449.65    70.3  2446.2    80.3 2443.12   110.5  2434.7   120.5 2432.32
   130.6 2430.74   140.6 2430.06   150.6 2429.75   361.5 2424.56   512.2 2420.59
   530.2  2420.3   542.2 2420.27   545.2 2420.27   752.7 2420.52  1053.4 2421.85
  1143.6 2422.91  1293.9  2423.2  1444.3 2425.11  1594.6 2425.28  1644.7  2425.8
  1674.8 2426.33  1724.9  2427.5    1785  2429.4  1825.1 2430.41  1855.2  2430.7
#Mann= 3 , 0 , 0
       0     .06       0   530.2    .045       0   545.2     .06       0
Bank Sta=530.2,545.2
XS Rating Curve= 0 ,0
Exp/Cntr=0.3,0.1

Type RM Length L Ch R = 1 ,8490.8  ,761.9,769.1,776.3
XS GIS Cut Line= 3
     2074148.762      342832.974     2074488.734      344379.601
     2075082.352       344798.88
#Sta/Elev= 30
       0 2439.45    10.1 2437.52    20.2 2436.57    40.4  2435.2   161.4 2429.47
   181.6 2428.82   272.3 2427.52   383.3 2425.29   494.2  2423.6   625.4 2420.92
   716.1 2419.79   756.5 2418.81   849.8 2418.38   857.3 2418.37   864.8 2418.37
   948.1 2418.52  1371.7 2421.57  1694.6 2423.35  1805.6  2423.7  1896.5 2424.36
  2037.8 2426.72    2058 2429.48  2068.1 2430.34  2128.6 2434.39  2158.9 2435.24
  2199.3 2435.07  2229.6 2434.47  2249.8 2433.77    2280 2431.12  2310.3 2430.92
#Mann= 3 , 0 , 0
       0     .06       0   849.8    .045       0   864.8     .06       0
Bank Sta=849.8,864.8
XS Rating Curve= 0 ,0
Exp/Cntr=0.3,0.1

Type RM Length L Ch R = 1 ,7721.6  ,950.2,958.7,961.1
XS GIS Cut Line= 4
     2073652.115      342820.048       2073638.9      343198.116
     2073619.153      343763.095     2073577.201      345020.926
#Sta/Elev= 30
       0 2450.53   109.5 2433.61   149.3 2432.67     219 2445.08   288.7 2447.01
   298.7 2448.45   358.4 2467.68   388.4 2472.81   408.6 2468.44   499.4 2432.64
   519.6 2428.03   671.1 2425.65   852.8 2419.97  1004.4 2418.38  1014.1 2418.37
  1019.4 2418.37  1215.5  2419.4  1306.1 2423.73  1457.1 2425.26  1577.9 2430.32
  1658.5 2435.24  1708.8 2447.91  1779.3 2456.19  1809.5    2455    1890 2446.98
  1910.2 2446.23  1970.6 2452.15  2041.1 2465.18  2131.7 2474.37  2202.2  2487.3
#Mann= 3 , 0 , 0
       0     .06       0  1004.4    .045       0  1019.4     .06       0
Bank Sta=1004.4,1019.4
XS Rating Curve= 0 ,0
Exp/Cntr=0.3,0.1

Type RM Length L Ch R = 1 ,6762.9  ,1046.2,1046.5,1026.7
XS GIS Cut Line= 4
     2073176.653      342721.365     2073159.999       342861.23
     2073089.074      343456.879     2072952.434      344604.414
#Sta/Elev= 30
       0 2522.68    90.6 2519.01   120.7 2517.03   260.8 2499.97   300.8 2494.11
   340.8 2483.69   380.8 2471.94   450.8 2447.54   480.8 2438.03   520.8 2430.36
   560.8 2421.45   570.8 2420.07   590.8 2419.05   720.7 2416.77   734.2 2416.79
   749.2 2416.94   861.3 2418.79   961.8 2419.35  1223.1 2417.71    1414 2424.86
  1514.5  2430.2  1534.6 2432.61  1594.9 2451.05    1625 2459.29  1645.1 2463.17
  1715.5 2465.52  1785.8  2463.7  1846.1 2464.77  1866.2 2465.87  1896.4 2469.48
#Mann= 3 , 0 , 0
       0     .06       0   734.2    .045       0   749.2     .06       0
#XS Ineff= 2 , 0
                          967.27          2419.4
Permanent Ineff=
       F       F
Bank Sta=734.2,749.2
XS Rating Curve= 0 ,0
Exp/Cntr=0.3,0.1

Type RM Length L Ch R = 1 ,5716.4  ,605.2,609.7,609.1
XS GIS Cut Line= 5
     2072360.717      342549.802     2072403.755      342794.805
     2072506.749      343381.124      2072712.99        344555.2
     2072718.926      344588.987
#Sta/Elev= 30
       0 2525.17   119.4 2516.59     189 2512.72   289.1  2509.3   309.3 2507.09
   369.8  2495.4   379.9 2492.36   400.1 2481.87   480.8 2435.83   490.9 2431.56
   511.1 2427.75   561.5 2422.22   622.1 2417.34   648.7 2416.68   663.7 2416.73
   924.2 2415.87  1465.1 2416.27  1495.2 2416.82  1535.2 2421.26  1545.3 2423.62
  1565.3 2429.98  1585.3 2434.72  1645.4    2444  1655.4 2444.69  1705.5 2445.32
  1825.7 2454.23  1925.9 2464.42    2006 2475.85  2044.7  2478.3  2070.4 2480.95
#Mann= 3 , 0 , 0
       0     .06       0   648.7    .045       0   663.7     .06       0
Bank Sta=648.7,663.7
XS Rating Curve= 0 ,0
Exp/Cntr=0.3,0.1

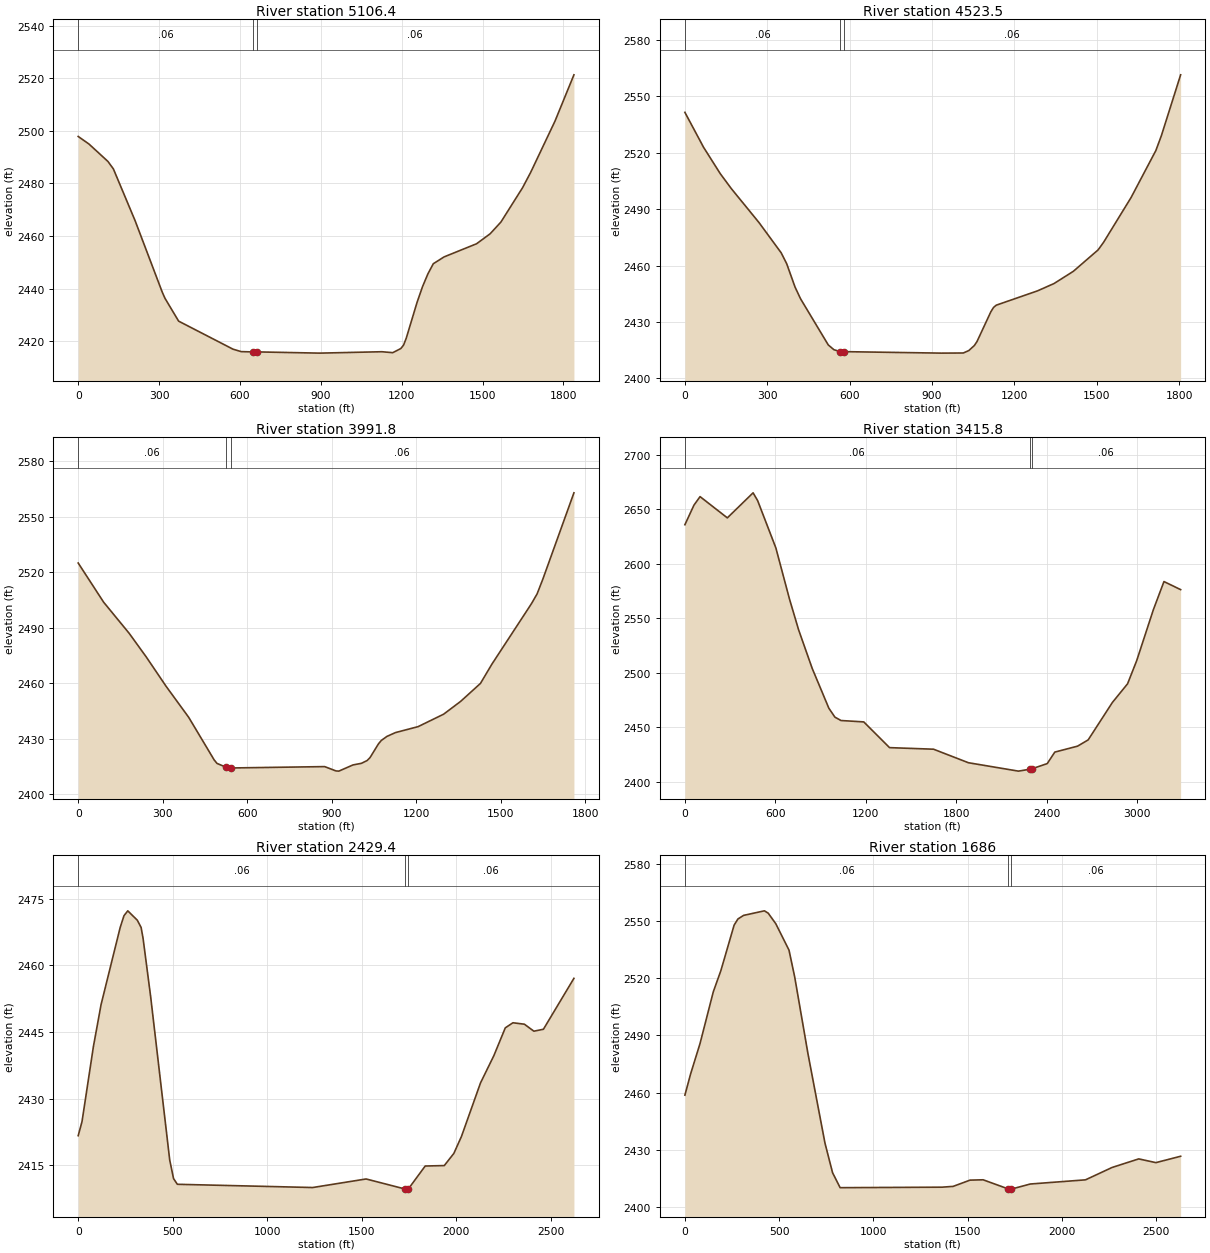
Type RM Length L Ch R = 1 ,5106.4  ,582.2,583.1,567
XS GIS Cut Line= 4
      2071936.22      342777.487     2071946.576       342836.44
      2072049.57      343422.759     2072254.433      344588.987
#Sta/Elev= 30
       0 2497.83    39.9 2494.96   110.3 2488.34   130.5 2485.51   211.2  2465.8
   312.1 2438.59   322.2 2436.28   372.6 2427.64   574.4 2416.98   604.7 2416.05
   646.9 2415.94   661.9 2415.95     896 2415.48  1126.8 2416.01  1166.9 2415.65
    1197 2417.23  1207.1 2418.52  1217.1 2421.15  1257.2 2434.77  1277.3  2440.7
  1297.4  2445.6  1317.4 2449.45  1357.6 2452.06    1478 2457.05  1528.2 2460.83
  1568.3  2465.3  1648.6 2478.34  1678.7 2484.18    1769 2503.67  1839.2 2521.26
#Mann= 3 , 0 , 0
       0     .06       0   646.9    .045       0   661.9     .06       0
Bank Sta=646.9,661.9
XS Rating Curve= 0 ,0
Exp/Cntr=0.3,0.1

Type RM Length L Ch R = 1 ,4523.5  ,532.8,531.7,561
XS GIS Cut Line= 4
      2071461.24      343015.467     2071474.683      343050.884
     2071685.934      343607.437     2072101.942      344703.433
#Sta/Elev= 30
       0 2541.46    68.2 2522.83   128.7 2508.89     169 2500.93     270 2482.86
   350.7 2466.79   370.8 2460.99   401.1 2448.62   421.3 2442.34   522.2 2417.83
   542.4 2415.33   564.3  2414.3   579.3 2414.27   933.8 2413.48  1013.9 2413.55
    1034 2414.84    1054 2417.48    1064 2419.66  1114.1  2435.4  1124.1 2437.76
  1134.2 2438.98  1284.4 2446.58  1344.6 2450.48  1414.7 2456.96  1504.9 2468.34
  1524.9 2472.38  1625.1  2496.2  1715.3 2521.17  1735.3 2529.02  1805.5  2561.4
#Mann= 3 , 0 , 0
       0     .06       0   564.3    .045       0   579.3     .06       0
Bank Sta=564.3,579.3
XS Rating Curve= 0 ,0
Exp/Cntr=0.3,0.1

Type RM Length L Ch R = 1 ,3991.8  ,575.4,576,597.3
XS GIS Cut Line= 2
      2071026.24      343216.554     2071825.844      344783.656
#Sta/Elev= 30
       0 2525.01    90.5 2503.81     181 2487.03   241.3 2474.33   311.6 2458.51
   392.1 2441.69   482.6 2418.66   492.6 2416.79     526 2414.64     541 2414.32
   874.6 2415.06   914.8 2412.73   924.9 2412.62   975.2 2415.96  1005.3 2416.84
  1025.4 2418.34  1035.5 2419.88  1065.6 2427.34  1075.7 2429.18  1095.8 2431.38
    1126 2433.44  1206.4 2436.65  1296.9 2443.37  1357.2 2450.28  1427.6 2459.99
  1467.8  2470.3  1608.5 2503.03  1628.6 2508.34  1648.7 2516.19  1759.3 2562.92
#Mann= 3 , 0 , 0
       0     .06       0     526    .045       0     541     .06       0
Bank Sta=526,541
XS Rating Curve= 0 ,0
Exp/Cntr=0.3,0.1

Type RM Length L Ch R = 1 ,3415.8  ,997.1,986.4,975.7
XS GIS Cut Line= 4
     2069769.703      342220.721     2070348.308      343128.386
     2070645.895      343595.215     2071575.835      345054.025
#Sta/Elev= 30
       0 2635.68    60.3 2653.65   100.6 2661.43   281.6 2641.94   452.5 2664.91
   482.7 2657.74   603.3 2614.49   693.8 2567.57   754.2 2539.37   844.7 2503.85
   955.3 2467.31   995.5 2459.14  1035.8 2456.06  1186.8 2454.79  1357.9 2431.19
  1649.7 2429.75    1881 2417.35    2213 2409.64  2287.1 2411.33  2302.1 2411.75
  2404.1 2416.55  2454.4  2427.1  2605.2 2432.54  2675.6 2438.27  2836.6 2472.66
  2937.2 2489.76  2997.5  2510.9  3108.1  2557.6  3178.6 2583.52  3289.2 2576.13
#Mann= 3 , 0 , 0
       0     .06       0  2287.1    .045       0  2302.1     .06       0
Bank Sta=2287.1,2302.1
XS Rating Curve= 0 ,0
Exp/Cntr=0.3,0.1

Type RM Length L Ch R = 1 ,2429.4  ,746.6,743.3,740.3
XS GIS Cut Line= 2
      2068860.63      343938.672     2071080.403      345333.478
#Sta/Elev= 30
       0 2421.62    20.2 2424.81    80.7 2441.79     121 2451.19   221.8 2468.53
     242 2471.21   262.2 2472.32   312.6  2470.2   332.7 2468.57   342.8 2466.19
   383.2 2452.96     484 2416.13   504.2 2411.95   524.3 2410.66  1240.2 2409.93
  1522.6 2411.86  1730.8 2409.57  1745.8  2409.6  1835.1 2414.78    1936 2414.88
  1986.4 2417.61  2026.7 2421.43  2127.5 2433.51  2198.1 2439.66  2258.6 2445.93
    2299 2447.08  2359.5 2446.76  2409.9 2445.18  2460.3 2445.62  2621.6  2457.1
#Mann= 3 , 0 , 0
       0     .06       0  1730.8    .045       0  1745.8     .06       0
Bank Sta=1730.8,1745.8
XS Rating Curve= 0 ,0
Exp/Cntr=0.3,0.1

Type RM Length L Ch R = 1 ,1686    ,766.1,767.1,767.1
XS GIS Cut Line= 4
     2068257.069      344665.708     2069311.967      345159.331
     2069806.503      345390.741     2070638.449      345780.036
#Sta/Elev= 30
       0 2458.72    30.1 2469.77    80.3 2485.78   150.6 2512.86   190.8 2523.96
     261 2547.78   281.1 2550.99   311.2 2552.89   421.7 2555.28   441.8 2554.06
   481.9 2548.55   552.2 2534.68   582.3 2520.66   652.6 2480.49     743 2433.56
   783.2 2418.08   823.3 2410.24  1363.2  2410.5  1422.8 2410.92  1512.1 2414.19
  1581.6 2414.37  1713.1 2409.66  1728.1 2409.49  1730.9 2409.48  1831.8 2412.16
  2124.5 2414.34  2265.8 2420.83  2407.1 2425.32    2498 2423.36  2629.2  2426.7
#Mann= 3 , 0 , 0
       0     .06       0  1713.1    .045       0  1728.1     .06       0
Bank Sta=1713.1,1728.1
XS Rating Curve= 0 ,0
Exp/Cntr=0.3,0.1

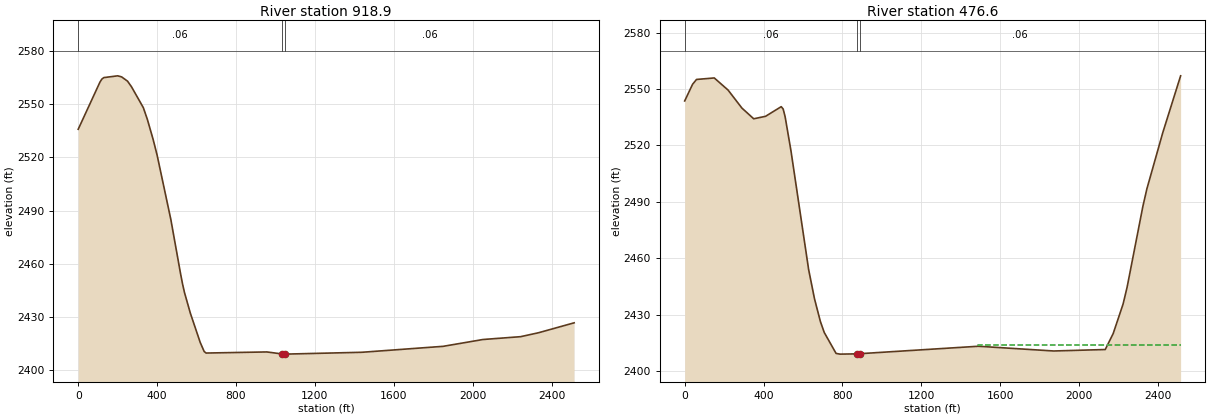
Type RM Length L Ch R = 1 ,918.9   ,436.6,442.4,448.7
XS GIS Cut Line= 4
     2068262.856      345353.568     2068627.086      345541.774
     2069112.155      345792.421     2070496.386      346507.687
#Sta/Elev= 30
       0 2535.81     110 2562.31     120 2564.08     130  2564.9     200  2565.9
     220  2565.3     250  2562.9     270 2559.76     330    2548     350 2541.58
     380    2530     400 2521.25   469.6    2485   519.2 2454.27   529.1 2448.61
     539 2443.75   568.8 2432.14   618.4 2415.81   638.3 2410.71   648.2  2409.8
     956 2410.42  1031.8 2409.31  1046.4 2409.19  1046.8 2409.19  1438.5 2410.23
  1850.6 2413.59  2051.7 2417.42  2242.7 2419.02  2333.2 2421.22  2514.1 2426.82
#Mann= 3 , 0 , 0
       0     .06       0  1031.8    .045       0  1046.8     .06       0
Bank Sta=1031.8,1046.8
XS Rating Curve= 0 ,0
Exp/Cntr=0.3,0.1

Type RM Length L Ch R = 1 ,476.6   ,457,476.5,496
XS GIS Cut Line= 4
     2068154.964      345505.313     2068465.486      345773.009
     2068879.028      346129.518     2070059.145      347146.879
#Sta/Elev= 30
       0 2543.69      40 2552.54      60 2555.13     150 2555.93     220 2549.48
     290 2539.92     350  2534.2     410 2535.52   489.4 2540.65   499.3 2539.39
   509.2  2535.3     539 2517.05   628.4 2453.96   658.2 2438.38     688 2426.31
   707.8 2420.44   767.4 2409.36   787.2 2408.97   872.8 2409.11   887.8  2409.2
  1488.8 2413.16  1870.7 2410.64  2132.1 2411.42  2172.3 2419.93  2222.6 2435.66
  2242.7 2444.52  2323.1 2487.76  2343.2 2496.96  2423.6  2526.8  2514.1 2557.06
#Mann= 3 , 0 , 0
       0     .06       0   872.8    .045       0   887.8     .06       0
#XS Ineff= 2 , 0
                         1487.97         2413.71
Permanent Ineff=
       F       F
Bank Sta=872.8,887.8
XS Rating Curve= 0 ,0
Exp/Cntr=0.3,0.1

Chan Stop Cuts=-1
Use User Specified Reach Order=0
Composite Channel Slope=5